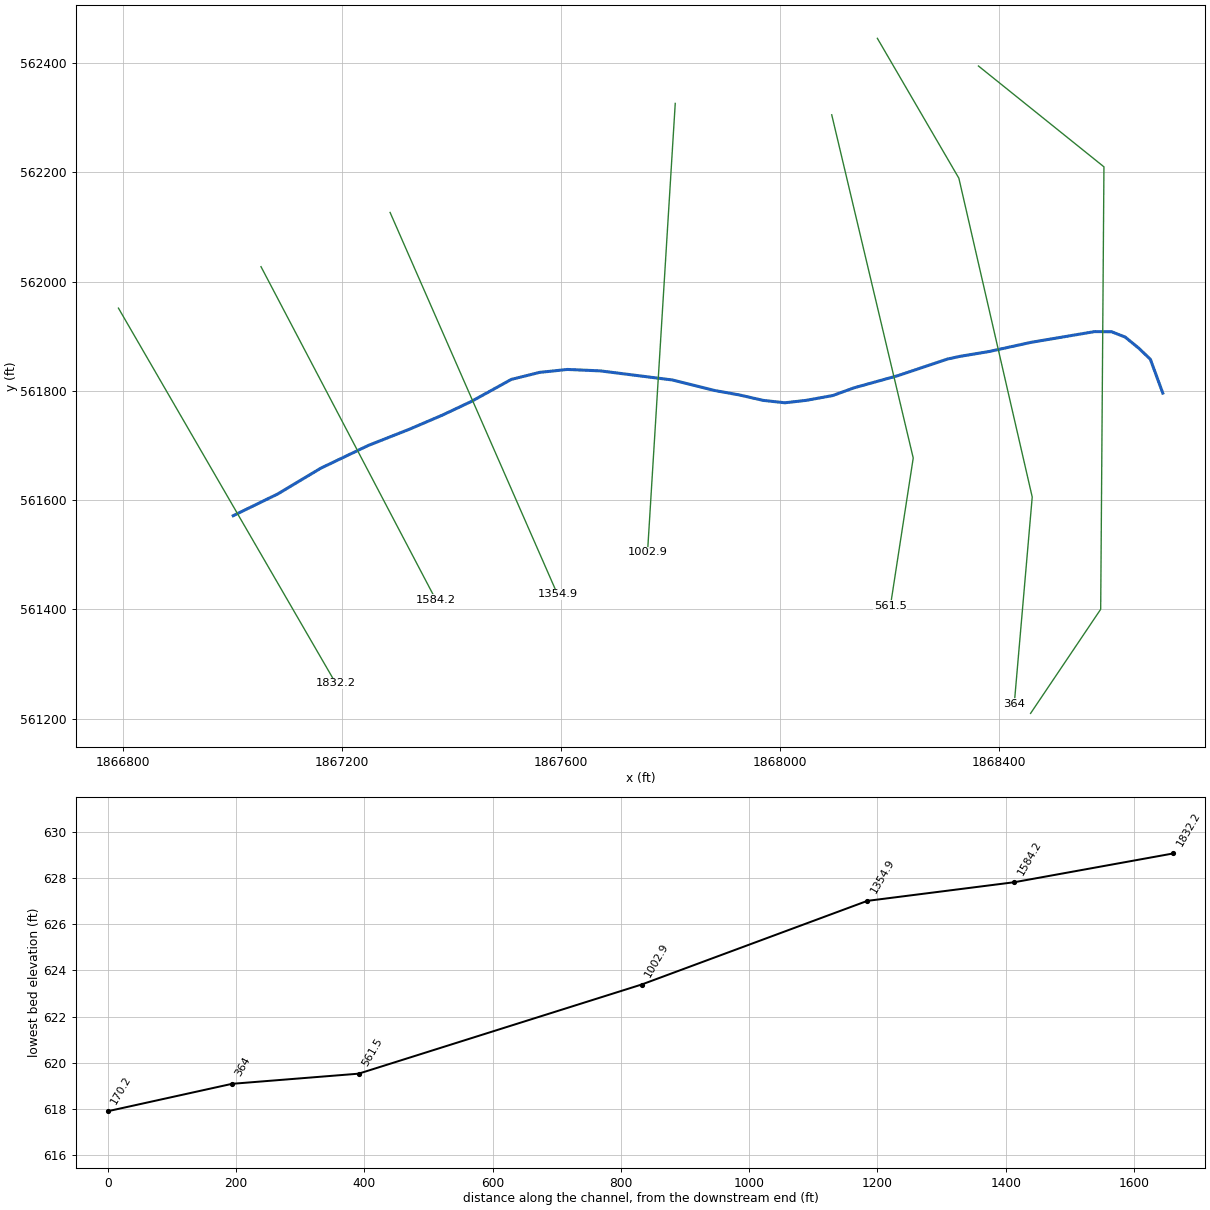
--- GabesCreek.prj (project) ---

Proj Title=GabesCreek
Current Plan=p01
Default Exp/Contr=0,0
English Units
Geom File=g01
Flow File=f01
Plan File=p01
BEGIN DESCRIPTION:
AMEC Environment & Infrastructure, 2013
Projection: NAD 1983 State Plane West Virginia South FIPS 4702 (US Feet)
Vertical Datum: NAVD 1988
END DESCRIPTION:
DSS Export Rating Curves= 0
DSS Export Rating Curve Sorted= 0
DSS Export Volume Flow Curves= 0
DXF OffsetX= 0
DXF OffsetY= 0
DXF ScaleX= 0
DXF ScaleY= 0

--- GabesCreek.p01 (plan) ---

Plan Title=Floodplain
Program Version=4.00
Geom File=g01
Flow File=f01
K Sum by GR=0
Std Step Tol=0.01
Critical Tol=0.01
Num of Std Step Trials=20
Max Error Tol=0.3
Flow Tol Ratio=0.001
Split Flow NTrial=30
Split Flow Tol=0.02
Split Flow Ratio=0.02
Log Output Level=0
Friction Slope Method=1
Unsteady Friction Slope Method=2
Unsteady Bridges Friction Slope Method=1
Global Log Level=0
CheckData=False
Run HTab=0
Run UNet=0
Run PostProcess=0
UNET Theta=0
UNET Theta Warmup=0
UNET ZTol=0
UNET ZSATol=0
UNET MxIter=0
UNET MaxInSteps=0
UNET DtIC=0
UNET DtMin=0
UNET MaxCRTS=0
UNET WFStab=0
UNET SFStab=0
UNET WFX=0
UNET SFX=0
UNET DSS MLevel=0
UNET DZMax Abort=0
UNET Convert EG Bridges=0
UNET Use Existing IB Tables=0
UNET Froude Limit=0
UNET Froude Power=0
Write IC File=0
Echo Input=False
Echo Output=False
Write Detailed=0

--- GabesCreek.f01 (steady flow) ---

Flow Title=NFF Regression Equation
Program Version=4.10
Number of Profiles= 1
Profile Names=P100yr
River Rch & RM=GabesCreek,Main            ,1832.2
1232.285
River Rch & RM=GabesCreek,Main            ,364
1250.705
River Rch & RM=GabesCreek,Main            ,170.2
1252.811
Boundary for River Rch & Prof#=GabesCreek,Main            , 1
Up Type= 0
Dn Type= 3
Dn Slope=0.00583
DSS Import GetInterval= 0
DSS Import GetPeak= 0
DSS Import FillOption= 0

--- GabesCreek.g01 (geometry) ---

Geom Title=USGS 3m DEM
Program Version=4.10

River Reach=GabesCreek      ,Main
Reach XY= 30
     1867000.724      561571.345     1867082.348      561611.292
     1867160.497      561658.185      1867247.33      561699.868
     1867322.007      561729.394     1867382.791      561755.446
     1867436.125      561780.673     1867508.653      561820.782
     1867559.931      561833.603     1867611.217      561839.037
      1867671.35      561836.385     1867803.068      561819.717
     1867879.483      561800.615      1867926.03      561792.169
     1867968.476      561782.442      1868008.27       561778.02
     1868047.179      561782.442     1868095.816      561791.285
     1868134.726      561805.434     1868214.313      561827.542
      1868304.97      561857.939     1868326.881      561862.749
     1868381.384      561871.835     1868457.497      561888.559
     1868574.156      561908.311     1868605.176      561908.013
     1868629.937      561898.286     1868654.697      561877.947
      1868675.92      561857.608     1868698.562      561795.781

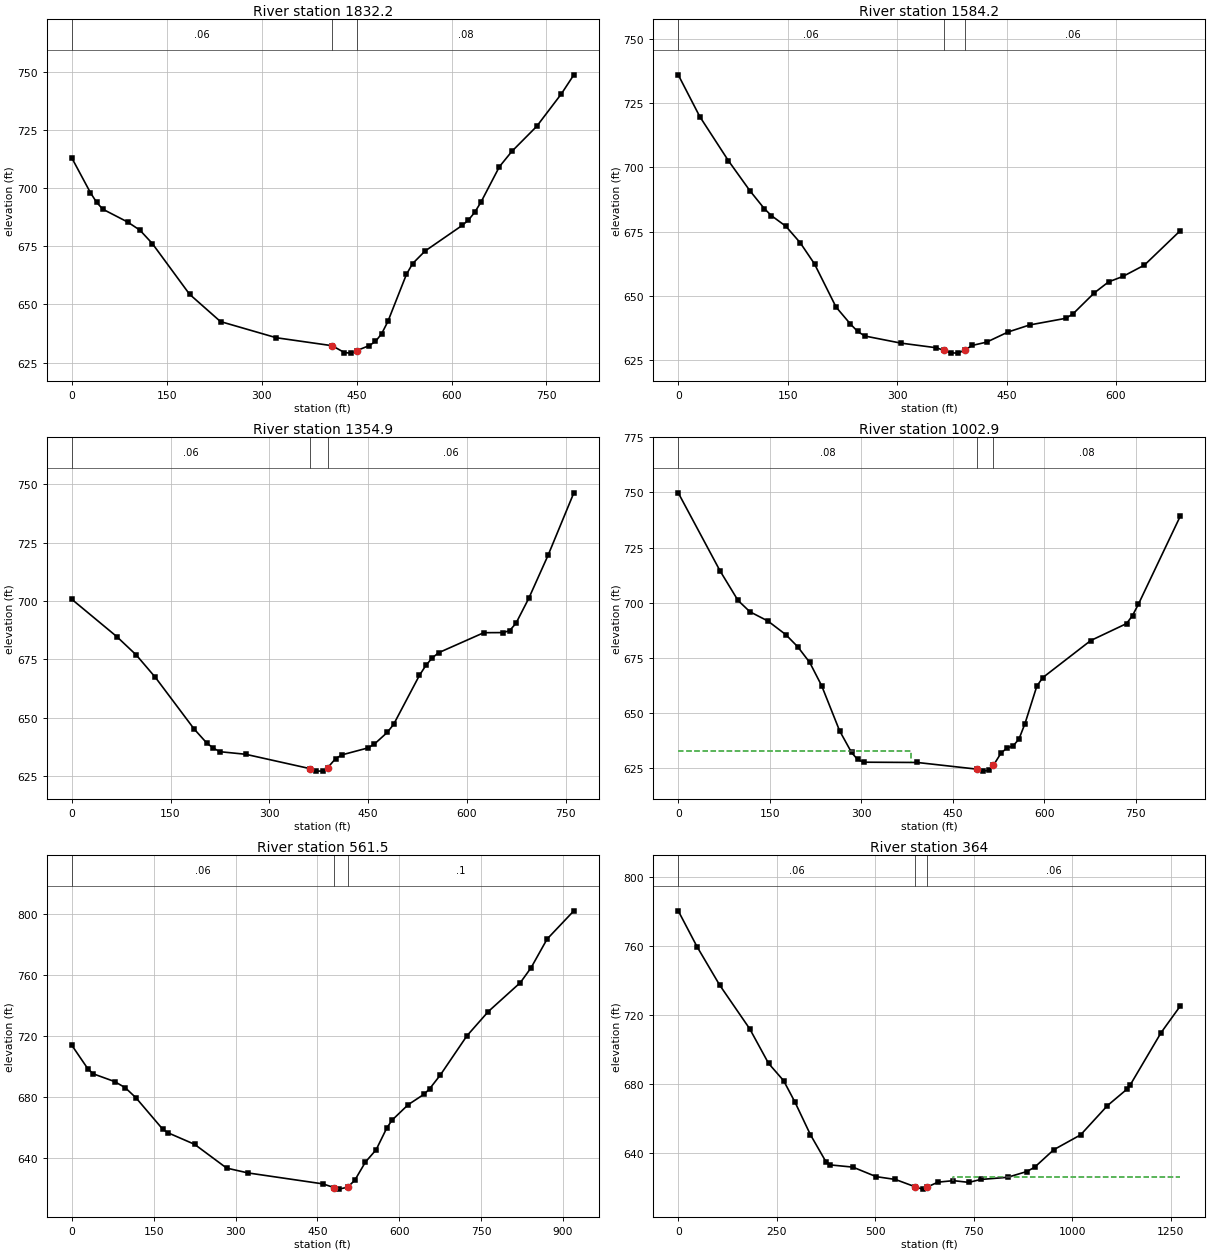
Type RM Length L Ch R = 1 ,1832.2  ,249.2,248,246.9
XS GIS Cut Line= 2
      1866791.04      561951.298     1867188.024      561264.516
#Sta/Elev= 30
       0  712.94    29.4  698.03    39.2  693.86      49   690.9    88.1  685.41
   107.7  681.89   127.3  676.13   186.1  654.37     235  642.63   323.2  635.69
   411.3  632.27   430.9  629.31   440.7  629.08   450.5  630.19   470.1  632.32
   479.9   634.1   489.7  637.46   499.5  642.69   528.8  662.91   538.6  667.55
   558.2  672.92     617  683.95   626.8  686.25   636.6  689.53   646.4  693.86
   675.7  709.15   695.3  715.71   734.5  726.44   773.7  740.47   793.3   748.6
#Mann= 3 , 0 , 0
       0     .06       0   411.3    .045       0   450.5     .08       0
Bank Sta=411.3,450.5
XS Rating Curve= 0 ,0
Exp/Cntr=0.3,0.1

Type RM Length L Ch R = 1 ,1584.2  ,231.2,229.3,227.4
XS GIS Cut Line= 2
     1867051.436       562027.16     1867370.761      561417.541
#Sta/Elev= 30
       0  735.98    29.5  719.76    68.8  702.59    98.3  690.91     118  683.97
   127.8  681.24   147.5  677.14   167.1  670.76   186.8  662.49   216.3  645.74
     236  639.14   245.8  636.29   255.6  634.49   304.8  631.74   353.9  629.91
   363.8  628.93   373.6  627.94   383.4  627.83   393.2  629.06   403.1  630.83
   422.7   632.1   452.2  636.05   481.7  638.78   530.9  641.34   540.7  642.97
   570.2  651.22   589.9  655.52   609.5  657.63     639  662.04   688.2  675.43
#Mann= 3 , 0 , 0
       0     .06       0   363.8    .045       0   393.2     .06       0
Bank Sta=363.8,393.2
XS Rating Curve= 0 ,0
Exp/Cntr=0.3,0.1

Type RM Length L Ch R = 1 ,1354.9  ,364.9,351.8,338.8
XS GIS Cut Line= 2
     1867287.211      562126.425     1867592.889      561427.733
#Sta/Elev= 30
       0  700.69    68.4  684.68    97.8  676.85   127.1  667.17   185.8  645.09
   205.3  638.98   215.1  636.86   224.9  635.35     264  634.25   361.8  628.09
   371.5  627.02   381.3  627.06   388.8  628.53   400.9  632.43   410.6  634.01
   449.8  636.96   459.5  638.58   479.1  643.59   488.9  647.08     528  668.04
   537.8  672.32   547.5  675.56   557.3  677.79   625.8  686.36   655.1  686.41
   664.9  687.22   674.6  690.34   694.2  701.14   723.5  719.58   762.6  746.32
#Mann= 3 , 0 , 0
       0     .06       0   361.8    .045       0   388.8     .06       0
Bank Sta=361.8,388.8
XS Rating Curve= 0 ,0
Exp/Cntr=0.3,0.1

Type RM Length L Ch R = 1 ,1002.9  ,433.1,441.3,449.4
XS GIS Cut Line= 2
     1867808.063      562326.014     1867757.448      561504.257
#Sta/Elev= 30
       0  749.85    68.6  714.37      98  700.96   117.6  695.79     147  691.61
   176.4  685.41     196  679.88   215.6  672.78   235.2  662.19   264.6  641.72
   284.2  631.86     294   628.7   303.8  627.45     392  627.32   490.1  624.28
   499.9  623.39   509.7  623.77   516.8  626.01   529.3  631.58   539.1  633.92
   548.9  634.76   558.7  637.96   568.5  644.91   588.1  662.07   597.9  665.91
   676.3  682.71   735.1  690.43   744.9  694.07   754.7   699.3   823.3  739.28
#Mann= 3 , 0 , 0
       0     .08       0   490.1    .045       0   516.8     .08       0
#XS Ineff= 2 , 0
          382.09  632.42
Permanent Ineff=
       F       F
Bank Sta=490.1,516.8
XS Rating Curve= 0 ,0
Exp/Cntr=0.3,0.1

Type RM Length L Ch R = 1 ,561.5   ,197.5,197.3,197.2
XS GIS Cut Line= 3
     1868093.892      562305.172     1868242.761      561676.945
     1868201.078      561406.003
#Sta/Elev= 30
       0  714.06    29.4   698.6    39.1  695.28    78.3   690.2    97.8  686.19
   117.4  679.59   166.3  659.01   176.1  656.55     225  648.95   283.7  633.34
   322.8  630.16   459.8  622.98   480.3  620.57   489.1  619.52   505.3  620.76
   518.5  625.35     538  637.31   557.6  645.39   577.2  659.74   586.9  664.88
   616.3  674.99   645.6  681.89   655.4  685.36     675  694.37     724  720.26
   763.1  736.17   821.8  755.17   841.4  764.91   870.8  783.78   919.8  802.32
#Mann= 3 , 0 , 0
       0     .06       0   480.3    .045       0   505.3      .1       0
Bank Sta=480.3,505.3
XS Rating Curve= 0 ,0
Exp/Cntr=0.3,0.1

Type RM Length L Ch R = 1 ,364     ,200.3,193.8,187.4
XS GIS Cut Line= 4
     1868177.259      562445.109     1868326.128      562189.055
      1868460.11      561605.488     1868427.359      561227.361
#Sta/Elev= 30
       0  780.64    47.8  759.79   105.1  737.56   181.5  712.12   229.3  692.07
   267.5  682.04   296.2  669.65   335.4  650.74   374.7  635.08   384.5  633.17
   443.4  631.85   502.3  626.34   551.4  624.68   600.5  620.52   620.1  619.08
   630.4  620.15   659.4  623.13   698.6     624   737.9  622.99   767.3  624.68
     836  625.94   885.1  629.31   904.7  631.79   953.3  641.96  1021.4  650.58
  1089.6  667.58  1138.2  676.93    1148  679.81  1225.8  709.96  1274.5   725.4
#Mann= 3 , 0 , 0
       0     .06       0   600.5    .045       0   630.4     .06       0
#XS Ineff= 2 , 0
                          698.51          625.98
Permanent Ineff=
       F       F
Bank Sta=600.5,630.4
XS Rating Curve= 0 ,0
Exp/Cntr=0.3,0.1

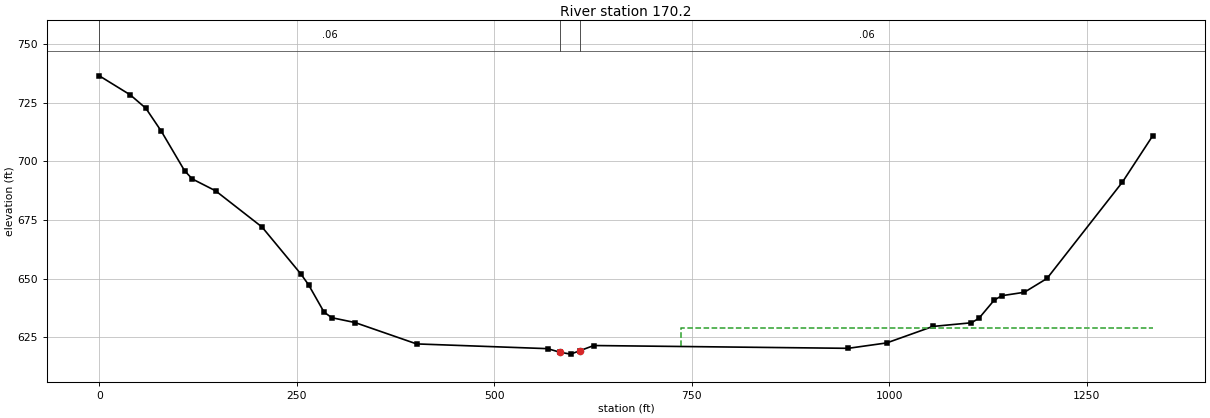
Type RM Length L Ch R = 1 ,170.2   ,204,170.1,136.3
XS GIS Cut Line= 4
     1868361.856      562394.494     1868591.115      562209.896
      1868585.16      561400.049     1868457.132      561209.496
#Sta/Elev= 30
       0   736.4    39.2  728.28    58.9  722.58    78.5  712.79   107.9  696.01
   117.7  692.48   147.2  687.43     206  672.01   255.1  652.05   264.9  647.43
   284.5  635.79   294.3   633.4   323.6  631.35   401.7  622.24   567.6  620.22
   583.6  618.66   596.8  617.89   608.6  619.38   626.1  621.55   948.1  620.36
   996.9  622.66  1055.4  629.68  1104.2  631.24  1113.8  633.17  1132.9  640.82
  1142.5  642.76  1171.2  644.23  1199.9  650.11  1295.5  691.19  1333.8  710.89
#Mann= 3 , 0 , 0
       0     .06       0   583.6    .045       0   608.6     .06       0
#XS Ineff= 2 , 0
                          736.39           629.1
Permanent Ineff=
       F       F
Bank Sta=583.6,608.6
XS Rating Curve= 0 ,0
Exp/Cntr=0.3,0.1

Chan Stop Cuts=-1
Use User Specified Reach Order=0
Composite Channel Slope=5